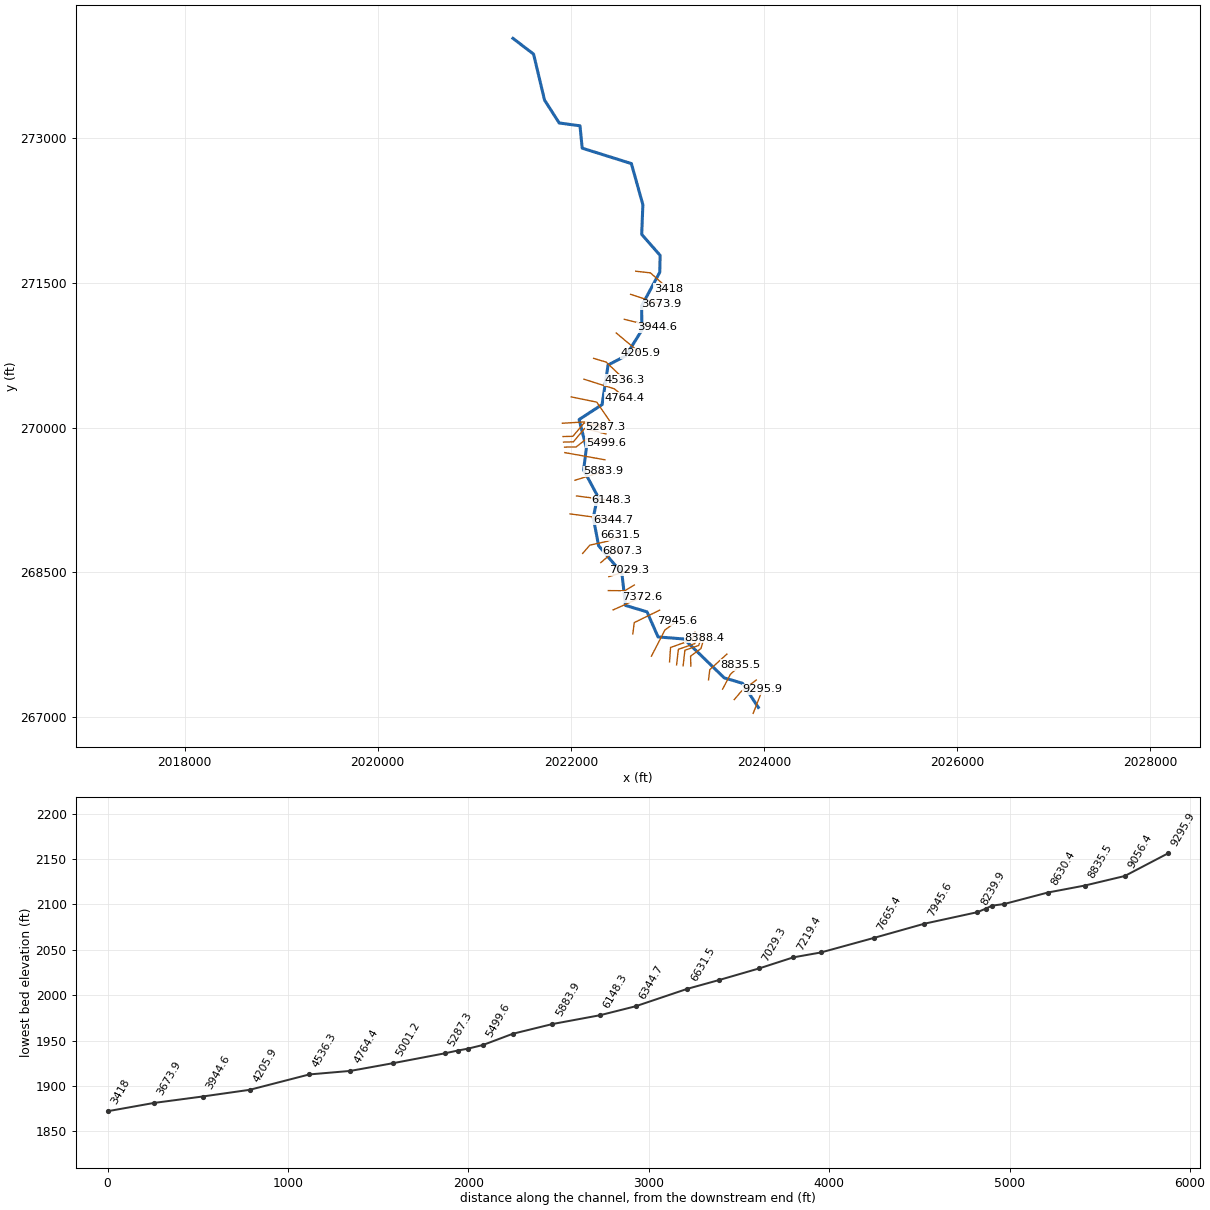
--- LRLCKTRIB.prj (project) ---

Proj Title=LRLCKTRIB
Current Plan=p01
Default Exp/Contr=0,0
English Units
Geom File=g01
Flow File=f01
Plan File=p01
BEGIN DESCRIPTION:
END DESCRIPTION:
DSS Export Rating Curves= 0
DSS Export Rating Curve Sorted= 0
DSS Export Volume Flow Curves= 0
DXF OffsetX= 0
DXF OffsetY= 0
DXF ScaleX= 0
DXF ScaleY= 0

--- LRLCKTRIB.p01 (plan) ---

Plan Title=Floodplain
Program Version=4.00
Geom File=g01
Flow File=f01
K Sum by GR=0
Std Step Tol=0.01
Critical Tol=0.01
Num of Std Step Trials=20
Max Error Tol=0.3
Flow Tol Ratio=0.001
Split Flow NTrial=30
Split Flow Tol=0.02
Split Flow Ratio=0.02
Log Output Level=0
Friction Slope Method=1
Unsteady Friction Slope Method=2
Unsteady Bridges Friction Slope Method=1
Global Log Level=0
CheckData=False
Run HTab=0
Run UNet=0
Run PostProcess=0
UNET Theta=0
UNET Theta Warmup=0
UNET ZTol=0
UNET ZSATol=0
UNET MxIter=0
UNET MaxInSteps=0
UNET DtIC=0
UNET DtMin=0
UNET MaxCRTS=0
UNET WFStab=0
UNET SFStab=0
UNET WFX=0
UNET SFX=0
UNET DSS MLevel=0
UNET DZMax Abort=0
UNET Convert EG Bridges=0
UNET Use Existing IB Tables=0
UNET Froude Limit=0
UNET Froude Power=0
Write IC File=0
Echo Input=False
Echo Output=False
Write Detailed=0

--- LRLCKTRIB.f01 (steady flow) ---

Flow Title=2010 USGS WV Regression Equation
Program Version=4.00
Number of Profiles=1
Profile Names=P100yr
River Rch & RM=LRLCKTRIB,Main      ,9295.9
513.3434
River Rch & RM=LRLCKTRIB,Main      ,8388.4
570.2559
River Rch & RM=LRLCKTRIB,Main      ,6807.3
592.5922
River Rch & RM=LRLCKTRIB,Main      ,6344.7
737.8326
River Rch & RM=LRLCKTRIB,Main      ,4205.9
799.6531
River Rch & RM=LRLCKTRIB,Main      ,2204.8
882.6356
River Rch & RM=LRLCKTRIB,Main      ,555.9
963.8991
River Rch & RM=LRLCKTRIB,Main      ,198.9
966.1209
Boundary for River Rch & Prof#=LRLCKTRIB,Main      ,1
Up Type=0
Dn Type=3
Dn Slope=0.02831

--- LRLCKTRIB.g01 (geometry) ---

Geom Title=LiDAR
Program Version=4.10

River Reach=LRLCKTRIB       ,Main
Reach XY= 30
     2023941.839      267098.322     2023776.925      267349.407
     2023588.901      267404.763     2023172.515      267808.436
     2022903.361      267829.537     2022788.773      268089.852
     2022566.563      268156.245     2022527.972      268493.652
     2022287.695      268774.902     2022232.325      269066.989
     2022277.972      269289.229     2022132.067      269561.791
     2022160.785      269789.659     2022085.687      270084.448
     2022323.528      270239.483     2022385.538      270649.926
     2022570.595       270746.63     2022735.014      271010.785
     2022733.484      271263.496     2022921.201      271612.576
     2022924.285      271787.622     2022733.701      272004.937
     2022745.952      272312.039     2022626.931      272739.312
     2022117.382      272899.034     2022094.813      273130.805
     2021879.535      273160.319     2021727.474      273397.642
      2021613.91      273874.729     2021400.103      274038.195

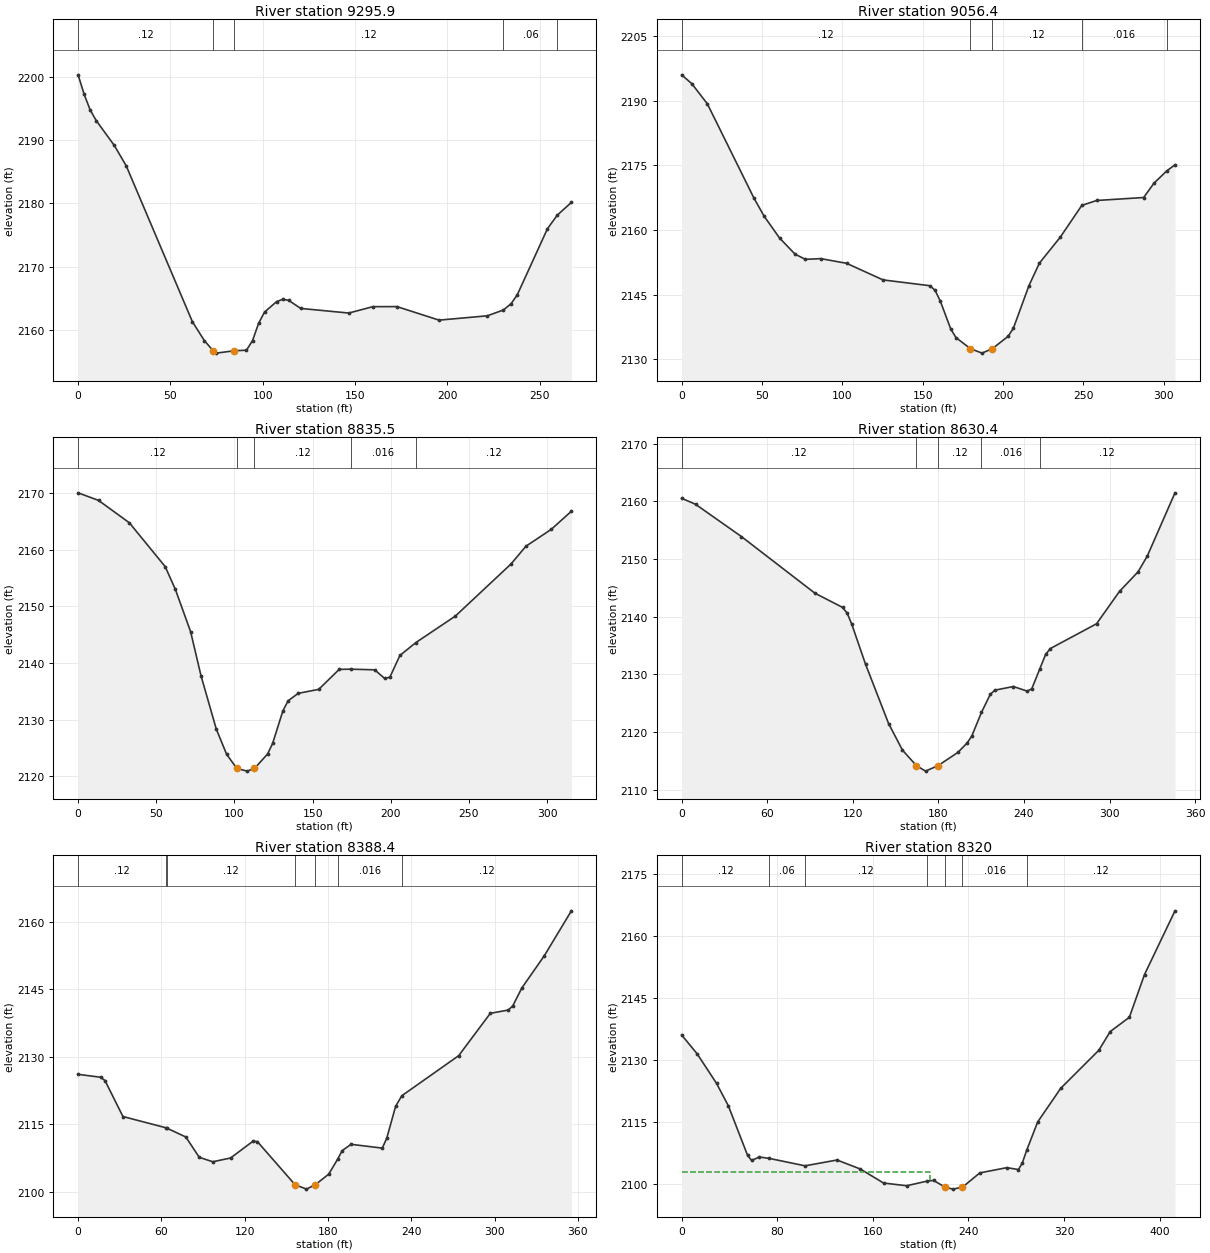
Type RM Length L Ch R = 1 ,9295.9  ,251.7,239.5,227.2
XS GIS Cut Line= 2
     2023888.126      267036.823     2023985.782      267285.521
#Sta/Elev= 30
       0 2200.34     3.3 2197.25     6.5 2194.82     9.8 2193.11    19.6 2189.18
    26.1 2185.93    61.9  2161.3    68.4  2158.3   73.16  2156.7    74.9 2156.32
    84.7  2156.7    91.2 2156.78    94.5 2158.31    97.8 2161.05     101 2162.82
   107.5 2164.46   110.8 2164.83     114 2164.68   120.6 2163.39   146.6 2162.66
   159.7 2163.67   172.7 2163.68   195.5 2161.54   221.6 2162.22  230.372163.142
   234.6 2164.16   237.9 2165.56   254.2 2175.98  259.562178.149   267.2 2180.16
#Mann= 5 ,-1 , 0
       0     .12       0   73.16    .045       0    84.7     .12       0
  230.37     .06       0  259.56    .016       0
Bank Sta=73.16,84.7
XS Rating Curve= 0 ,0
Exp/Cntr=0.3,0.1

Type RM Length L Ch R = 1 ,9056.4  ,210.6,220.9,230.6
XS GIS Cut Line= 3
     2023692.813      267180.052     2023763.126      267263.385
     2023920.678      267383.177
#Sta/Elev= 30
       0 2196.04     6.4 2193.95      16 2189.29    44.9 2167.46    51.3 2163.21
    60.9 2158.14    70.6 2154.37      77 2153.18    86.6 2153.34   102.6 2152.26
   125.3  2148.4   154.5 2147.05   157.7 2145.99     161 2143.44   167.4 2137.04
   170.7    2135  179.622132.446   186.9 2131.39   193.4 2132.44   203.1 2135.28
   206.4 2137.14   216.1 2147.05   222.6 2152.29   235.6 2158.32  249.022165.713
   258.3 2166.85   287.5 2167.54     294  2170.9  301.852173.717     307 2175.14
#Mann= 5 ,-1 , 0
       0     .12       0  179.62    .045       0   193.4     .12       0
  249.02    .016       0  301.85     .12       0
Bank Sta=179.62,193.4
XS Rating Curve= 0 ,0
Exp/Cntr=0.3,0.1

Type RM Length L Ch R = 1 ,8835.5  ,212.7,205.1,197
XS GIS Cut Line= 3
      2023571.72      267288.125     2023652.449      267441.771
     2023756.615      267538.125
#Sta/Elev= 30
       0 2170.03    13.1 2168.69    32.8 2164.74    55.7 2157.01    62.2    2153
      72 2145.49    78.6 2137.76    88.4 2128.32      95 2123.89   101.5 2121.39
   108.1 2120.91   112.82121.375   121.2 2123.94   124.4 2125.79     131 2131.56
   134.3 2133.32   140.8 2134.64   153.9 2135.34     167 2138.87  174.442138.907
   189.7 2138.79   196.1 2137.26   199.4 2137.49   205.8 2141.32  216.022143.599
   241.3 2148.28   276.8 2157.45   286.4  2160.6   302.6 2163.58   315.5 2166.78
#Mann= 5 ,-1 , 0
       0     .12       0   101.5    .045       0   112.8     .12       0
  174.44    .016       0  216.02     .12       0
Bank Sta=101.5,112.8
XS Rating Curve= 0 ,0
Exp/Cntr=0.3,0.1

Type RM Length L Ch R = 1 ,8630.4  ,244.3,242,239.3
XS GIS Cut Line= 3
     2023425.886      267384.479     2023438.907      267489.948
      2023615.99      267651.406
#Sta/Elev= 30
       0 2160.54     9.7 2159.51    41.9  2153.9    93.4 2144.08   112.8 2141.61
     116 2140.64   119.2 2138.74   128.9 2131.77   145.1 2121.45   154.8 2116.85
   164.6 2114.15     171  2113.2  179.842114.164   193.7 2116.45   200.2  2118.1
   203.4 2119.28  210.232123.403   216.4 2126.53   219.6 2127.25   232.6 2127.88
   242.3 2127.08   245.5  2127.5  251.07 2130.91   255.2 2133.46   258.5 2134.47
   290.9 2138.77     307 2144.39     320 2147.78   326.5 2150.53   345.9 2161.49
#Mann= 5 ,-1 , 0
       0     .12       0   164.6    .045       0  179.84     .12       0
  210.23    .016       0  251.07     .12       0
Bank Sta=164.6,179.84
XS Rating Curve= 0 ,0
Exp/Cntr=0.3,0.1

Type RM Length L Ch R = 1 ,8388.4  ,75.2,68.4,58.6
XS GIS Cut Line= 4
     2023242.424      267527.424     2023240.192      267630.824
     2023346.763       267708.28     2023381.615      267823.281
#Sta/Elev= 30
       0 2126.07    16.2 2125.43    19.4 2124.68    32.3 2116.69   63.12  2114.2
   64.242114.056    77.6 2112.14    87.3 2107.61      97 2106.63   109.8 2107.46
   125.9 2111.18   129.1 2111.12   156.22101.544   164.5 2100.54   170.9 2101.53
   180.5 2103.87  186.952107.201   190.2  2109.1   196.6 2110.51   219.1 2109.66
   222.3 2111.86   228.7 2118.96  233.152121.309   274.1 2130.22   296.9 2139.64
   309.9 2140.38   313.1 2141.32   319.6 2145.28   335.8 2152.46   355.3 2162.44
#Mann= 7 ,-1 , 0
       0     .12       0   63.12     .06       0   64.24     .12       0
   156.2    .045       0   170.9     .12       0  186.95    .016       0
  233.15     .12       0
Bank Sta=156.2,170.9
XS Rating Curve= 0 ,0
Exp/Cntr=0.3,0.1

Type RM Length L Ch R = 1 ,8320    ,33.5,33.7,36.4
XS GIS Cut Line= 4
     2023162.865      267530.313     2023181.095      267691.771
     2023324.324       267741.25     2023355.574         267835.
#Sta/Elev= 30
       0 2136.07      13 2131.48    29.2 2124.32      39 2118.93    55.2 2106.84
    58.5 2105.64      65 2106.47   73.472106.125   103.22104.333     130 2105.74
   149.5 2103.56   168.9 2100.16   188.3  2099.5  205.172100.615   210.8 2100.79
   220.5 2099.14     227 2098.68  234.942099.142   249.5 2102.62   272.1 2103.89
   281.8 2103.43     285 2104.99  288.672108.077   297.9 2114.98   317.2 2123.14
   349.1 2132.37   358.6  2136.9   374.6 2140.35   387.3 2150.73   412.8 2166.18
#Mann= 7 ,-1 , 0
       0     .12       0   73.47     .06       0   103.2     .12       0
  205.17    .016       0   220.5    .045       0  234.94    .016       0
  288.67     .12       0
#XS Ineff= 2 , 0
          207.95 2102.84
Permanent Ineff=
       F       F
Bank Sta=220.5,234.94
XS Rating Curve= 0 ,0
Exp/Cntr=0.3,0.1

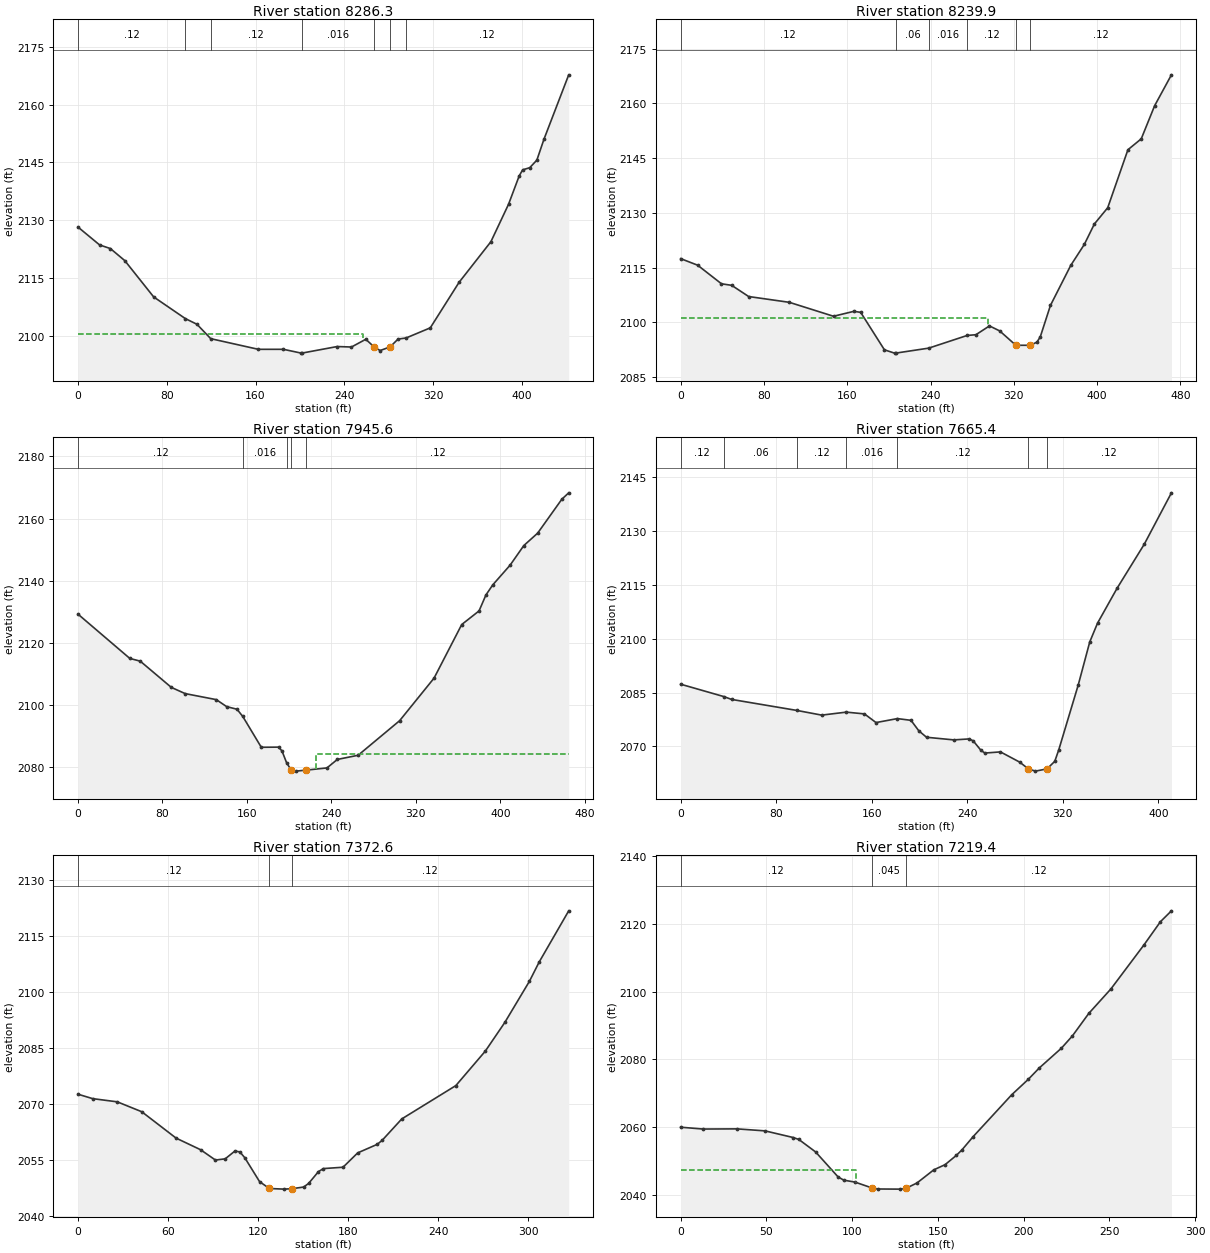
Type RM Length L Ch R = 1 ,8286.3  ,46.7,46.4,46.6
XS GIS Cut Line= 4
     2023095.157      267539.427     2023113.386      267700.885
     2023283.959      267760.781     2023315.209      267854.531
#Sta/Elev= 30
       0 2128.22    19.5 2123.57    29.2 2122.63    42.2 2119.49    68.2 2110.06
   96.772104.421   107.2 2102.95  119.622099.207   162.5 2096.44   185.1 2096.44
   201.2 2095.45  201.762095.457   233.5 2097.16   246.4 2097.04   259.3 2099.05
  266.572097.119   272.2 2096.12  281.212097.073   288.4 2099.11  295.532099.382
   317.4 2102.02   343.3 2113.84     372 2124.41   387.9 2134.14   397.5 2141.52
   400.6 2143.08     407 2143.65   413.4 2145.61   419.8 2151.04   442.1 2167.78
#Mann= 7 ,-1 , 0
       0     .12       0   96.77     .06       0  119.62     .12       0
  201.76    .016       0  266.57    .045       0  281.21    .016       0
  295.53     .12       0
#XS Ineff= 2 , 0
          256.97 2100.41
Permanent Ineff=
       F       F
Bank Sta=266.57,281.21
XS Rating Curve= 0 ,0
Exp/Cntr=0.3,0.1

Type RM Length L Ch R = 1 ,8239.9  ,276.3,294.3,311.6
XS GIS Cut Line= 4
      2023022.24      267570.677     2023032.657      267720.417
     2023256.615      267799.844     2023286.563      267877.969
#Sta/Elev= 30
       0 2117.46    16.3 2115.66    39.2 2110.56      49 2110.14    65.3 2107.07
   104.4 2105.48   146.8 2101.66   166.4 2103.01   172.9 2102.73   195.7 2092.46
   205.4 2091.55  206.892091.568  238.232092.917  275.172096.394   283.6  2096.6
   296.6 2099.01   306.4 2097.65  321.982093.701   335.6  2093.7   342.2 2094.56
   345.4    2096   355.2 2104.65   374.7 2115.61   387.7 2121.35   397.4 2126.97
   410.2 2131.42   429.6 2147.32   442.4 2150.31   455.3 2159.41   471.4 2167.86
#Mann= 6 ,-1 , 0
       0     .12       0  206.89     .06       0  238.23    .016       0
  275.17     .12       0  321.98    .045       0   335.6     .12       0
#XS Ineff= 2 , 0
          295.15 2101.11
Permanent Ineff=
       F       F
Bank Sta=321.98,335.6
XS Rating Curve= 0 ,0
Exp/Cntr=0.3,0.1

Type RM Length L Ch R = 1 ,7945.6  ,294.5,280.2,265.6
XS GIS Cut Line= 3
      2022834.74      267630.573     2022974.063      267901.406
      2023102.97      267996.458
#Sta/Elev= 30
       0  2129.3    49.1 2115.05      59 2114.17    88.4 2105.74   101.5 2103.74
     131  2101.8   140.8 2099.55   150.6 2098.71  156.092096.378   173.6 2086.48
     190 2086.53   193.2 2085.29  197.532081.535  202.022079.088   206.3 2078.81
   216.1 2079.13   235.8 2079.84   245.6 2082.57   265.3 2083.91   304.6 2095.03
   337.2 2108.72   363.4 2125.95   379.8 2130.33   386.3 2135.45   392.8 2138.71
   409.2 2145.04   422.2 2151.35   435.3 2155.34   458.2 2166.25   464.7  2168.3
#Mann= 5 ,-1 , 0
       0     .12       0  156.09    .016       0  197.53     .12       0
  202.02    .045       0   216.1     .12       0
#XS Ineff= 2 , 0
                          225.49         2084.32
Permanent Ineff=
       F       F
Bank Sta=202.02,216.1
XS Rating Curve= 0 ,0
Exp/Cntr=0.3,0.1

Type RM Length L Ch R = 1 ,7665.4  ,293.3,292.8,291.8
XS GIS Cut Line= 3
     2022642.032      267861.042     2022656.355      267978.229
     2022919.376      268107.135
#Sta/Elev= 30
       0 2087.31   36.242083.859    42.6 2083.08   97.452080.007   118.1 2078.71
  138.692079.543   153.9 2079.05   163.6 2076.64  181.492077.744   192.9 2077.26
   199.4 2074.36   205.9 2072.55   228.7 2071.82   241.7 2072.09     245 2071.55
   251.5  2068.9   254.8 2068.16   267.8 2068.48     284 2065.62  291.232063.736
   297.1 2063.13   306.8 2063.75   313.3 2065.86   316.6 2069.01   332.9 2087.04
   342.6 2099.08   349.1 2104.29   365.4 2113.96   388.2 2126.23     411 2140.55
#Mann= 7 ,-1 , 0
       0     .12       0   36.24     .06       0   97.45     .12       0
  138.69    .016       0  181.49     .12       0  291.23    .045       0
   306.8     .12       0
Bank Sta=291.23,306.8
XS Rating Curve= 0 ,0
Exp/Cntr=0.3,0.1

Type RM Length L Ch R = 1 ,7372.6  ,162.8,153.2,143.3
XS GIS Cut Line= 2
     2022437.605       268109.74     2022735.782      268243.854
#Sta/Elev= 30
       0  2072.6     9.8 2071.41    26.2 2070.55    42.5  2067.9    65.4 2060.82
    81.7 2057.71    91.6 2054.94    98.1 2055.26   104.6 2057.36   107.9 2057.12
   111.2 2055.54     121 2049.16   127.5 2047.31   137.3 2047.14   142.5 2047.25
   150.4  2047.7   153.7 2048.67   160.2 2051.82   163.5 2052.65   176.6 2053.01
   186.4 2056.86   199.4 2059.15   202.7 2060.23   215.8 2065.98   251.8 2074.91
   271.4 2084.14   284.4 2091.83   300.8 2102.87   307.3 2108.04     327 2121.78
#Mann= 3 ,-1 , 0
       0     .12       0   127.5    .045       0   142.5     .12       0
Bank Sta=127.5,142.5
XS Rating Curve= 0 ,0
Exp/Cntr=0.3,0.1

Type RM Length L Ch R = 1 ,7219.4  ,182.9,190.1,196.9
XS GIS Cut Line= 3
     2022388.126       268310.26     2022558.699      268308.958
     2022657.657      268368.854
#Sta/Elev= 30
       0 2060.01    13.1 2059.47    32.8 2059.52    49.2 2058.93    65.6 2056.97
    68.9  2056.4    78.7 2052.71    91.8 2045.34    95.1 2044.39   101.7 2043.81
   111.5  2042.1   114.8 2041.78   127.9 2041.74   131.2 2041.93   137.8 2043.55
   147.6 2047.43   154.2 2048.96   160.7 2051.67     164  2053.3   170.6 2057.25
   193.1 2069.61   202.7 2074.13   209.1 2077.48     222 2083.31   228.4 2086.92
     238 2093.59   250.9 2100.81   270.2 2113.82   279.8 2120.66   286.2 2123.86
#Mann= 3 ,-1 , 0
       0     .12       0   111.5    .045       0   131.2     .12       0
#XS Ineff= 2 , 0
          102.48 2047.26
Permanent Ineff=
       F       F
Bank Sta=111.5,131.2
XS Rating Curve= 0 ,0
Exp/Cntr=0.3,0.1

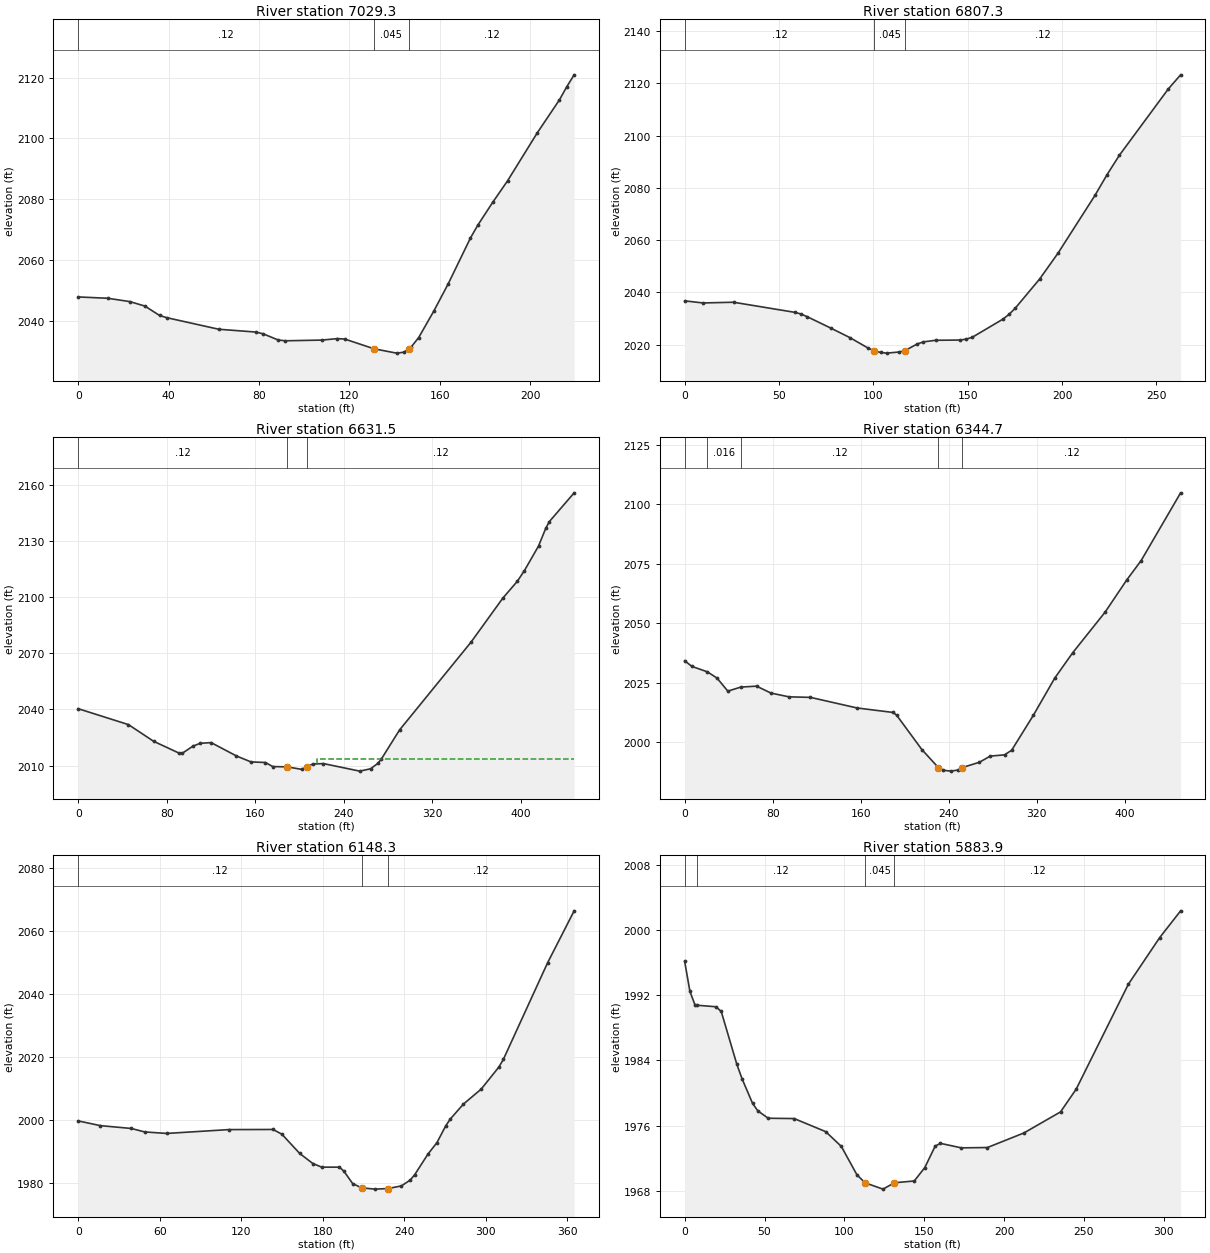
Type RM Length L Ch R = 1 ,7029.3  ,212.5,222,230.7
XS GIS Cut Line= 2
     2022393.334      268454.792      2022602.97      268519.896
#Sta/Elev= 30
       0 2047.96    13.1 2047.52    22.9 2046.42    29.5 2044.96      36 2041.88
    39.3 2041.13    62.2 2037.35    78.6 2036.43    81.9 2035.84    88.5 2033.82
    91.7 2033.56   108.1  2033.8   114.7 2034.28     118 2034.12     131 2030.92
   140.9 2029.51   144.2 2029.81  146.262030.888   147.2 2031.38   150.7 2034.64
   157.3  2043.2   163.8 2052.32   173.6 2067.31   176.9 2071.58   183.5 2079.07
     190 2086.05   203.1 2101.74     213 2112.68   216.2 2116.93   219.5 2120.88
#Mann= 3 ,-1 , 0
       0     .12       0     131    .045       0  146.26     .12       0
Bank Sta=131,146.26
XS Rating Curve= 0 ,0
Exp/Cntr=0.3,0.1

Type RM Length L Ch R = 1 ,6807.3  ,186.7,175.7,164.2
XS GIS Cut Line= 3
     2022310.001      268600.625     2022431.095       268703.49
     2022532.657      268725.625
#Sta/Elev= 30
       0 2036.72     9.7 2035.92    25.9 2036.19    58.4 2032.32    61.6  2031.7
    64.8  2030.7    77.8 2026.16    87.6 2022.63    97.3  2018.6   100.5  2017.6
   103.8 2016.97     107 2016.71   113.5 2017.13   116.7 2017.66   123.2  2020.2
   126.5 2021.02     133 2021.63   145.9 2021.72   149.2 2022.07   152.4 2022.78
   168.6  2029.7   171.9 2031.57   175.1 2033.85   188.1 2045.09   197.9 2055.05
   217.4 2077.08   223.8 2085.01   230.4 2092.51   256.3 2117.87   262.8 2123.25
#Mann= 3 ,-1 , 0
       0     .12       0   100.5    .045       0   116.7     .12       0
Bank Sta=100.5,116.7
XS Rating Curve= 0 ,0
Exp/Cntr=0.3,0.1

Type RM Length L Ch R = 1 ,6631.5  ,294.5,286.9,278.2
XS GIS Cut Line= 4
     2022122.501      268695.677      2022196.72      268781.615
     2022379.011      268821.979     2022513.126      268884.479
#Sta/Elev= 30
       0 2040.41    45.4  2031.9    68.1    2023    90.8 2016.75    94.1  2016.6
   103.8 2020.44   110.3  2021.9   120.1 2022.28     143 2015.14   156.1 2011.97
   169.2 2011.64   175.8 2009.47   188.9  2009.3     202 2007.97  206.642009.291
   211.8 2010.81   221.6 2011.07   254.4 2007.03   264.2 2008.28   270.8 2011.17
     274 2013.53   290.4 2029.04   354.9 2075.92   383.9 2099.66   396.8  2108.5
   403.2  2114.2     416 2127.37   422.5 2136.82   425.7  2140.4   448.2 2155.84
#Mann= 3 ,-1 , 0
       0     .12       0   188.9    .045       0  206.64     .12       0
#XS Ineff= 2 , 0
                           216.2         2013.78
Permanent Ineff=
       F       F
Bank Sta=188.9,206.64
XS Rating Curve= 0 ,0
Exp/Cntr=0.3,0.1

Type RM Length L Ch R = 1 ,6344.7  ,196.3,196.4,196.5
XS GIS Cut Line= 2
      2021990.99      269105.833     2022437.605      269045.938
#Sta/Elev= 30
       0 2034.18     6.5 2031.83   20.692029.512    29.4  2026.9    39.2 2021.41
   51.022023.121    65.3 2023.51    78.4  2020.6    94.7 2019.02   114.3 2018.79
   156.7 2014.33   189.4 2012.45   192.6 2011.29   215.5 1996.86  230.511989.279
   235.1 1988.16   241.6 1987.79   248.2 1988.23   252.1 1989.27   267.8 1991.52
   277.6  1994.1   290.6 1994.63   297.1 1996.58   316.7 2011.19   336.3 2026.94
   352.6 2037.58     382 2054.63   401.6 2068.12   414.7 2076.27   450.6 2104.77
#Mann= 5 ,-1 , 0
       0     .12       0   20.69    .016       0   51.02     .12       0
  230.51    .045       0   252.1     .12       0
Bank Sta=230.51,252.1
XS Rating Curve= 0 ,0
Exp/Cntr=0.3,0.1

Type RM Length L Ch R = 1 ,6148.3  ,254.4,264.4,274.1
XS GIS Cut Line= 2
     2022058.699      269292.031     2022420.678      269245.156
#Sta/Elev= 30
       0 1999.66    16.3 1998.16    39.1 1997.26    48.9 1996.16    65.2 1995.68
   110.8  1996.9   143.4 1996.94   149.9 1995.44     163 1989.32   172.7 1986.11
   179.2 1984.96   192.3 1984.96   195.5 1983.69     202 1979.73   208.6 1978.37
   218.4 1977.97   227.9 1978.14   237.9    1979   244.4 1980.87   247.7 1982.59
   257.5 1989.18     264 1992.74   270.5  1998.1   273.8 2000.24   283.5 2005.01
   296.6 2009.78   309.6 2016.79   312.9 2019.23   345.4  2049.9     365 2066.47
#Mann= 3 ,-1 , 0
       0     .12       0   208.6    .045       0   227.9     .12       0
Bank Sta=208.6,227.9
XS Rating Curve= 0 ,0
Exp/Cntr=0.3,0.1

Type RM Length L Ch R = 1 ,5883.9  ,230.6,220.2,209.1
XS GIS Cut Line= 2
     2022041.772      269454.792     2022338.647      269545.938
#Sta/Elev= 30
       0 1996.13     3.3 1992.45     6.5 1990.78    7.411990.769    19.6 1990.58
    22.9    1990    32.7  1983.5      36 1981.72    42.5 1978.74    45.8 1977.82
    52.3 1976.91    68.6 1976.87    88.3 1975.27    98.1 1973.46   107.9 1969.97
  112.991968.995   124.2 1968.22   131.4    1969   143.8 1969.22   150.4 1970.87
   156.9  1973.5   160.2 1973.83   173.3 1973.28   189.6 1973.32   212.5 1975.11
   235.4 1977.69   245.2 1980.48   277.9 1993.35   297.5 1999.06   310.6 2002.34
#Mann= 4 ,-1 , 0
       0    .016       0    7.41     .12       0  112.99    .045       0
   131.4     .12       0
Bank Sta=112.99,131.4
XS Rating Curve= 0 ,0
Exp/Cntr=0.3,0.1

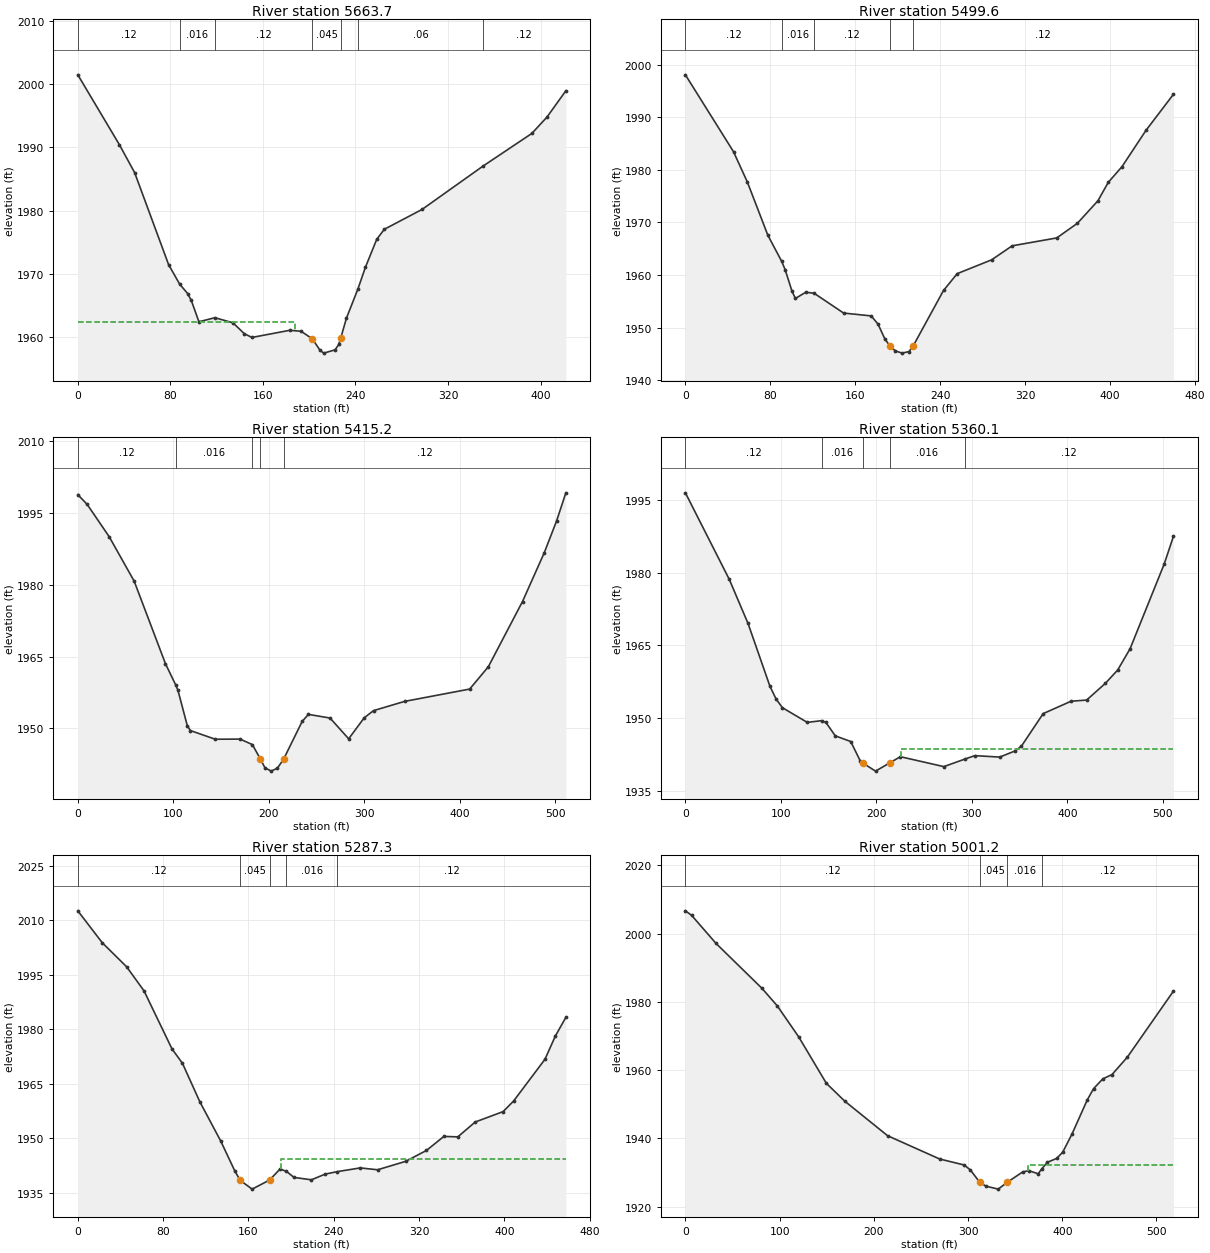
Type RM Length L Ch R = 1 ,5663.7  ,144.3,164.1,182.9
XS GIS Cut Line= 2
     2021937.605       269741.25      2022352.97      269667.031
#Sta/Elev= 30
       0 2001.49      36 1990.42    49.1 1986.03    78.5 1971.46   87.961968.404
    94.9  1966.9    98.1  1965.8   104.7 1962.43  118.461963.072   134.1 1962.27
   143.9 1960.55   150.5 1959.95   183.2 1961.08     193 1960.93   202.8 1959.72
   209.3 1957.94   212.6 1957.47   222.4 1957.99   225.6 1958.85  227.19 1959.79
   232.2 1962.99  242.131967.613   248.6 1971.04   258.4 1975.47   264.9 1977.05
   297.6  1980.2  350.111987.032   392.5 1992.22   405.6 1994.81   421.9 1998.97
#Mann= 7 ,-1 , 0
       0     .12       0   87.96    .016       0  118.46     .12       0
   202.8    .045       0  227.19     .12       0  242.13     .06       0
  350.11     .12       0
#XS Ineff= 2 , 0
          187.82 1962.47
Permanent Ineff=
       F       F
Bank Sta=202.8,227.19
XS Rating Curve= 0 ,0
Exp/Cntr=0.3,0.1

Type RM Length L Ch R = 1 ,5499.6  ,77.2,84.4,92
XS GIS Cut Line= 4
     2021935.001      269798.542     2022054.792      269799.844
     2022161.563      269884.479     2022360.782      269842.813
#Sta/Elev= 30
       0 1998.04    45.3 1983.44    58.3  1977.7    77.7 1967.55    90.7  1962.6
    93.9 1961.05   100.4 1956.94   103.6 1955.56   113.3 1956.74  121.16 1956.56
     149 1952.79     175 1952.25   181.4 1950.69   187.9 1947.85   192.6 1946.57
   197.6 1945.62   204.1 1945.18   210.6 1945.48  214.611946.585   243.1 1957.09
     256 1960.28   288.4  1962.9   307.7 1965.56   349.7 1967.06   369.1 1969.83
   388.5 1974.12   398.2 1977.61   411.1 1980.58   433.7 1987.48   459.6 1994.34
#Mann= 5 ,-1 , 0
       0     .12       0    90.7    .016       0  121.16     .12       0
   192.6    .045       0  214.61     .12       0
Bank Sta=192.6,214.61
XS Rating Curve= 0 ,0
Exp/Cntr=0.3,0.1

Type RM Length L Ch R = 1 ,5415.2  ,53.6,55.2,57
XS GIS Cut Line= 4
     2021924.584      269850.625     2022026.147      269853.229
     2022143.334      269992.552     2022363.386       269935.26
#Sta/Elev= 30
       0 1998.88     9.8 1996.84    32.8  1990.1      59 1980.79    91.8 1963.51
  102.621959.032   104.8 1957.99   114.6 1950.59   117.8 1949.55   143.9 1947.73
   169.9 1947.76   182.81946.608   191.21943.571   195.9 1941.78   202.4 1941.06
   208.9 1941.67   215.4 1943.54   234.9 1951.45   241.4 1952.93   264.1 1952.16
   283.6 1947.82   299.9 1952.22   309.6 1953.71   342.1 1955.64   410.3 1958.22
   429.8 1962.88   465.6 1976.53   488.3 1986.69   501.3 1993.38     511 1999.26
#Mann= 5 ,-1 , 0
       0     .12       0  102.62    .016       0   182.8     .12       0
   191.2    .045       0   215.4     .12       0
Bank Sta=191.2,215.4
XS Rating Curve= 0 ,0
Exp/Cntr=0.3,0.1

Type RM Length L Ch R = 1 ,5360.1  ,95.3,72.8,49.6
XS GIS Cut Line= 4
     2021919.376      269907.917     2022020.938      269910.521
     2022138.126      270049.844     2022358.178      269992.552
#Sta/Elev= 30
       0 1996.53    45.9 1978.67    65.6 1969.54    88.5 1956.58      95 1953.92
   101.6 1952.14   127.6 1949.11  142.581949.464   147.1 1949.11   156.9 1946.33
   173.1 1945.16   182.9 1941.22   186.1 1940.67   199.1 1939.04  213.791940.728
   225.1 1942.02   270.6 1939.97  292.361941.512   303.1 1942.24   329.1 1941.94
   345.4 1943.23   351.9 1944.22   374.6 1950.92   403.8 1953.48   420.1 1953.72
   439.6 1957.15   452.6 1959.92   465.6 1964.32   501.3 1981.81     511 1987.53
#Mann= 5 ,-1 , 0
       0     .12       0  142.58    .016       0   186.1    .045       0
  213.79    .016       0  292.36     .12       0
#XS Ineff= 2 , 0
                          225.39          1943.6
Permanent Ineff=
       F       F
Bank Sta=186.1,213.79
XS Rating Curve= 0 ,0
Exp/Cntr=0.3,0.1

Type RM Length L Ch R = 1 ,5287.3  ,309.4,286,262.7
XS GIS Cut Line= 3
     2021911.563      270045.938     2022175.886      270061.563
     2022360.782      270006.875
#Sta/Elev= 30
       0 2012.56    22.9 2003.78    45.8 1997.14    62.1 1990.51    88.3 1974.54
    98.1 1970.58   114.4 1959.99     134 1949.17   147.1    1941  152.19 1938.37
   163.4 1935.93   179.8 1938.43   189.6 1941.47  195.651940.814   202.7 1939.15
     219  1938.5   232.1 1940.08  243.471940.754   264.8 1941.77   281.1 1941.26
   307.3 1943.57   326.9 1946.58   343.2 1950.44   356.3 1950.32   372.6 1954.41
   398.8 1957.28   408.6 1960.19     438 1971.68   447.8 1978.11   457.6 1983.23
#Mann= 5 ,-1 , 0
       0     .12       0  152.19    .045       0   179.8     .12       0
  195.65    .016       0  243.47     .12       0
#XS Ineff= 2 , 0
                           190.4         1944.16
Permanent Ineff=
       F       F
Bank Sta=152.19,179.8
XS Rating Curve= 0 ,0
Exp/Cntr=0.3,0.1

Type RM Length L Ch R = 1 ,5001.2  ,221.3,236.9,251.8
XS GIS Cut Line= 3
     2022004.011      270319.375     2022268.334      270264.688
     2022408.959       270060.26
#Sta/Elev= 30
       0  2006.7     6.5 2005.41    32.5 1997.15    81.3 1983.97    97.6 1978.81
   120.3 1969.73   149.6 1956.14   169.1 1950.91   214.6 1940.77   269.9 1933.94
     296 1932.18   302.6 1930.69   312.4 1927.11   318.9 1925.99     332 1925.11
   341.8 1927.15   358.1 1930.17   364.6 1930.52   374.4 1929.61  378.511931.127
   384.2 1932.98     394  1934.1   400.5 1935.95   410.3 1941.24   426.6  1951.3
   433.2 1954.56     443 1957.43   452.8  1958.7   469.1 1963.81     518 1983.16
#Mann= 4 ,-1 , 0
       0     .12       0   312.4    .045       0   341.8    .016       0
  378.51     .12       0
#XS Ineff= 2 , 0
                          363.47         1932.16
Permanent Ineff=
       F       F
Bank Sta=312.4,341.8
XS Rating Curve= 0 ,0
Exp/Cntr=0.3,0.1

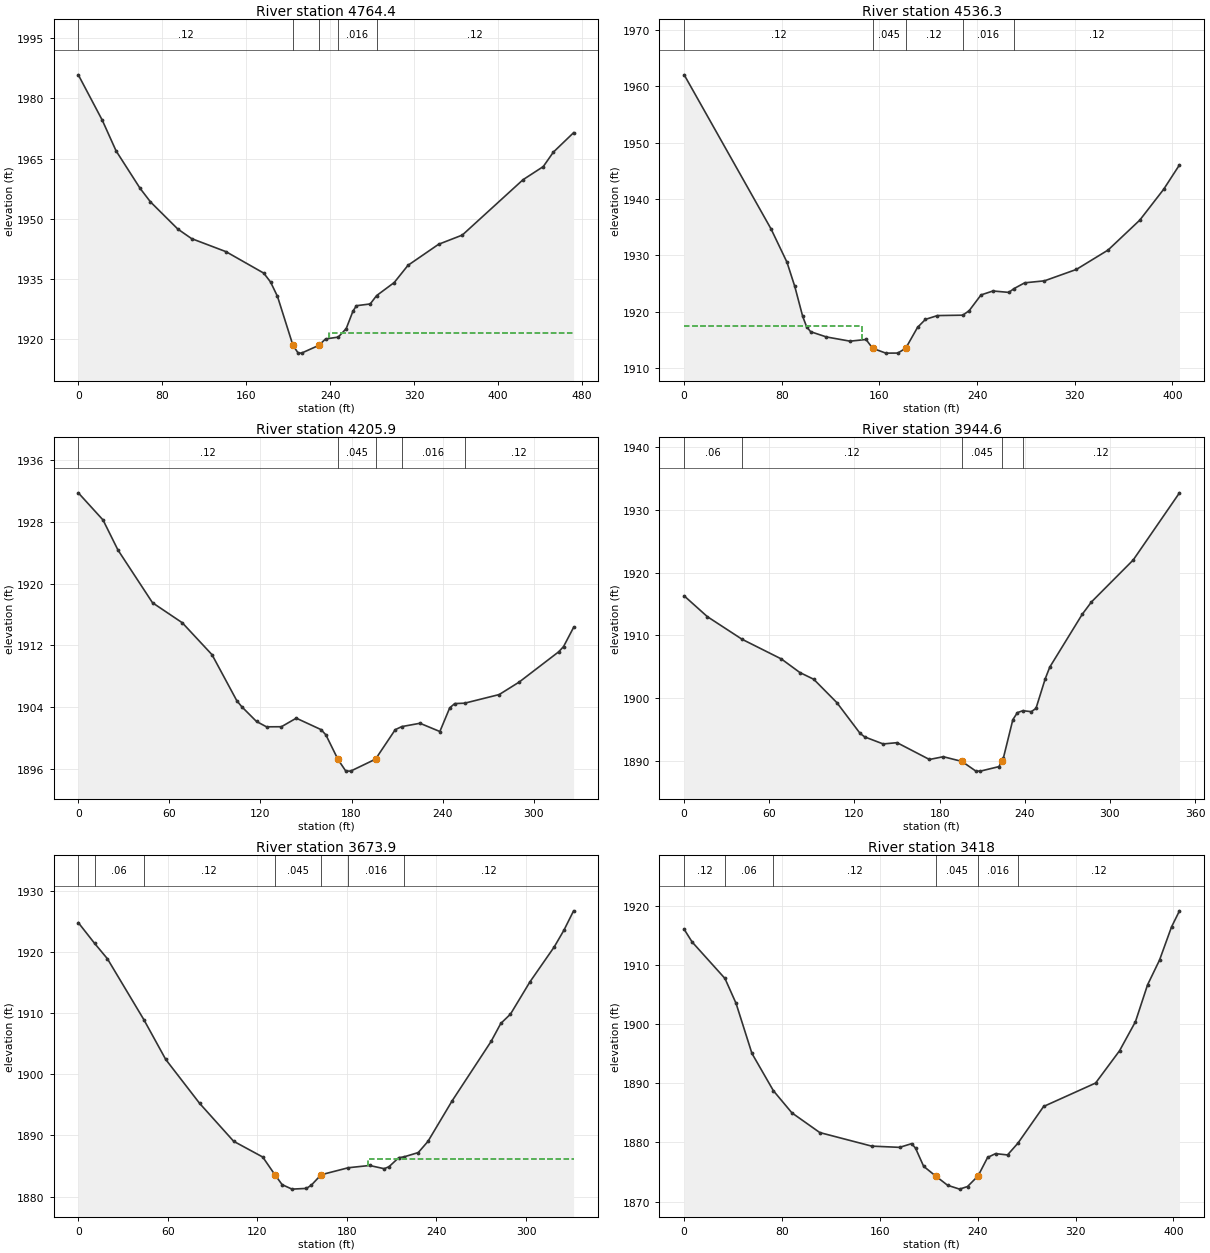
Type RM Length L Ch R = 1 ,4764.4  ,238.1,228.1,217.2
XS GIS Cut Line= 3
     2022135.522      270502.969     2022450.626      270402.708
     2022560.001      270312.865
#Sta/Elev= 30
       0 1985.83    22.9 1974.51      36 1966.91    58.9 1957.58    68.8 1954.21
    94.9 1947.44     108 1945.07   140.8 1941.82   176.8 1936.48   183.3 1934.26
   189.9 1930.68  204.591918.543   209.5 1916.62   212.8 1916.57   229.2 1918.49
   235.7 1920.09  247.811920.562   255.4 1922.66   261.9 1927.05   265.2 1928.37
   278.3 1928.81  284.411930.892   301.2 1934.14   314.3 1938.42   343.5 1943.66
   366.1 1945.95     424 1959.73   443.3    1963   452.9 1966.59   472.2 1971.43
#Mann= 5 ,-1 , 0
       0     .12       0  204.59    .045       0   229.2     .12       0
  247.81    .016       0  284.41     .12       0
#XS Ineff= 2 , 0
                          238.91         1921.49
Permanent Ineff=
       F       F
Bank Sta=204.59,229.2
XS Rating Curve= 0 ,0
Exp/Cntr=0.3,0.1

Type RM Length L Ch R = 1 ,4536.3  ,328.5,330.5,330.8
XS GIS Cut Line= 3
     2022235.782      270719.115      2022365.99      270680.052
     2022561.303      270493.854
#Sta/Elev= 30
       0 1962.02    71.2 1934.68    84.2  1928.8    90.6 1924.51    97.1 1919.18
   100.3 1917.35   103.6 1916.47   116.5 1915.54   135.9 1914.79     149 1915.09
  154.421913.523   165.2 1912.67     175 1912.68   181.5 1913.53   191.2 1917.24
   197.7 1918.66   207.5 1919.33  228.291919.401   233.5  1920.2   243.2 1922.99
     253 1923.69     266 1923.44   270.11924.097     279 1925.14   295.2 1925.49
   321.3 1927.51   347.3 1930.95   373.3 1936.26   392.8 1941.71   405.8 1946.05
#Mann= 5 ,-1 , 0
       0     .12       0  154.42    .045       0   181.5     .12       0
  228.29    .016       0   270.1     .12       0
#XS Ineff= 2 , 0
          146.03  1917.5
Permanent Ineff=
       F       F
Bank Sta=154.42,181.5
XS Rating Curve= 0 ,0
Exp/Cntr=0.3,0.1

Type RM Length L Ch R = 1 ,4205.9  ,251,261.3,271.6
XS GIS Cut Line= 2
     2022470.157      270982.135     2022720.157        270772.5
#Sta/Elev= 30
       0 1931.77    16.3 1928.25    26.1 1924.37    48.9 1917.53    68.5 1914.94
    88.1  1910.8   104.4 1904.85   107.7 1904.06   117.4 1902.15     124 1901.46
   133.8 1901.47   143.6 1902.58   159.9  1901.1   163.1 1900.42  171.061897.242
   176.2 1895.73   179.4 1895.72   195.8 1897.27   208.8 1901.09   213.11901.488
   225.1 1901.92   238.2 1900.85   244.7 1903.92     248 1904.47  254.541904.521
   277.3 1905.64   290.4 1907.25   316.5 1911.18   319.7 1911.86   326.3 1914.34
#Mann= 5 ,-1 , 0
       0     .12       0  171.06    .045       0   195.8     .12       0
   213.1    .016       0  254.54     .12       0
Bank Sta=171.06,195.8
XS Rating Curve= 0 ,0
Exp/Cntr=0.3,0.1

Type RM Length L Ch R = 1 ,3944.6  ,272.2,270.7,269
XS GIS Cut Line= 2
      2022553.49      271124.063     2022892.032      271039.427
#Sta/Elev= 30
       0 1916.31    16.3    1913   40.771909.388    68.5 1906.24    81.5 1904.08
    91.3    1903   107.6 1899.27   123.9 1894.38   127.2  1893.8   140.2 1892.68
     150 1892.88   172.8  1890.2   182.6 1890.64   195.7 1889.89   205.5 1888.35
   208.7 1888.34   221.8 1889.06  223.671889.907     225 1890.51   231.6 1896.56
   234.8 1897.68   238.71897.986   244.6 1897.83   247.9 1898.36   254.4 1903.08
   257.6 1904.94   280.5 1913.38     287 1915.35   316.4 1922.04     349 1932.76
#Mann= 5 ,-1 , 0
       0     .06       0   40.77     .12       0   195.7    .045       0
  223.67    .016       0   238.7     .12       0
Bank Sta=195.7,223.67
XS Rating Curve= 0 ,0
Exp/Cntr=0.3,0.1

Type RM Length L Ch R = 1 ,3673.9  ,265.1,255.9,246.5
XS GIS Cut Line= 2
     2022618.595      271383.177     2022933.699       271279.01
#Sta/Elev= 30
       0 1924.81   10.861921.435    19.5  1918.9   43.931908.933    58.6 1902.42
    81.3 1895.24   104.1 1889.04   123.6 1886.46  131.661883.595   136.6 1881.94
   143.2 1881.21   152.9 1881.33   156.2 1881.87   162.7 1883.56  180.931884.709
   195.2 1885.08     205 1884.55   208.2 1884.88   214.7 1886.35  218.441886.502
   227.8 1887.19   234.3 1889.02   250.5 1895.65   276.6 1905.37   283.1 1908.31
   289.6 1909.84   302.6  1915.1   318.9 1920.83   325.4 1923.56   331.9 1926.74
#Mann= 7 ,-1 , 0
       0     .12       0   10.86     .06       0   43.93     .12       0
  131.66    .045       0   162.7     .12       0  180.93    .016       0
  218.44     .12       0
#XS Ineff= 2 , 0
                          194.32         1886.17
Permanent Ineff=
       F       F
Bank Sta=131.66,162.7
XS Rating Curve= 0 ,0
Exp/Cntr=0.3,0.1

Type RM Length L Ch R = 1 ,3418    ,247.8,268.8,289.4
XS GIS Cut Line= 3
      2022671.98       271622.76     2022824.324      271605.833
     2023011.824      271437.865
#Sta/Elev= 30
       0 1916.01     6.5 1913.87   33.351907.705    42.4 1903.51    55.4 1895.04
   72.96 1888.73    88.1 1884.99   110.9 1881.66   153.3 1879.37   176.2 1879.16
     186 1879.79   189.2 1879.01   195.8 1875.96   205.6 1874.32   215.4 1872.75
   225.2  1872.1   231.7 1872.54   240.31874.332   248.1 1877.45   254.6  1878.1
   264.4 1877.88  272.95 1879.88   293.9 1886.07   336.4 1890.03     356 1895.49
     369  1900.4   378.9 1906.63   388.7 1910.82   398.5 1916.42     405 1919.14
#Mann= 6 ,-1 , 0
       0     .12       0   33.35     .06       0   72.96     .12       0
   205.6    .045       0   240.3    .016       0  272.95     .12       0
Bank Sta=205.6,240.3
XS Rating Curve= 0 ,0
Exp/Cntr=0.3,0.1