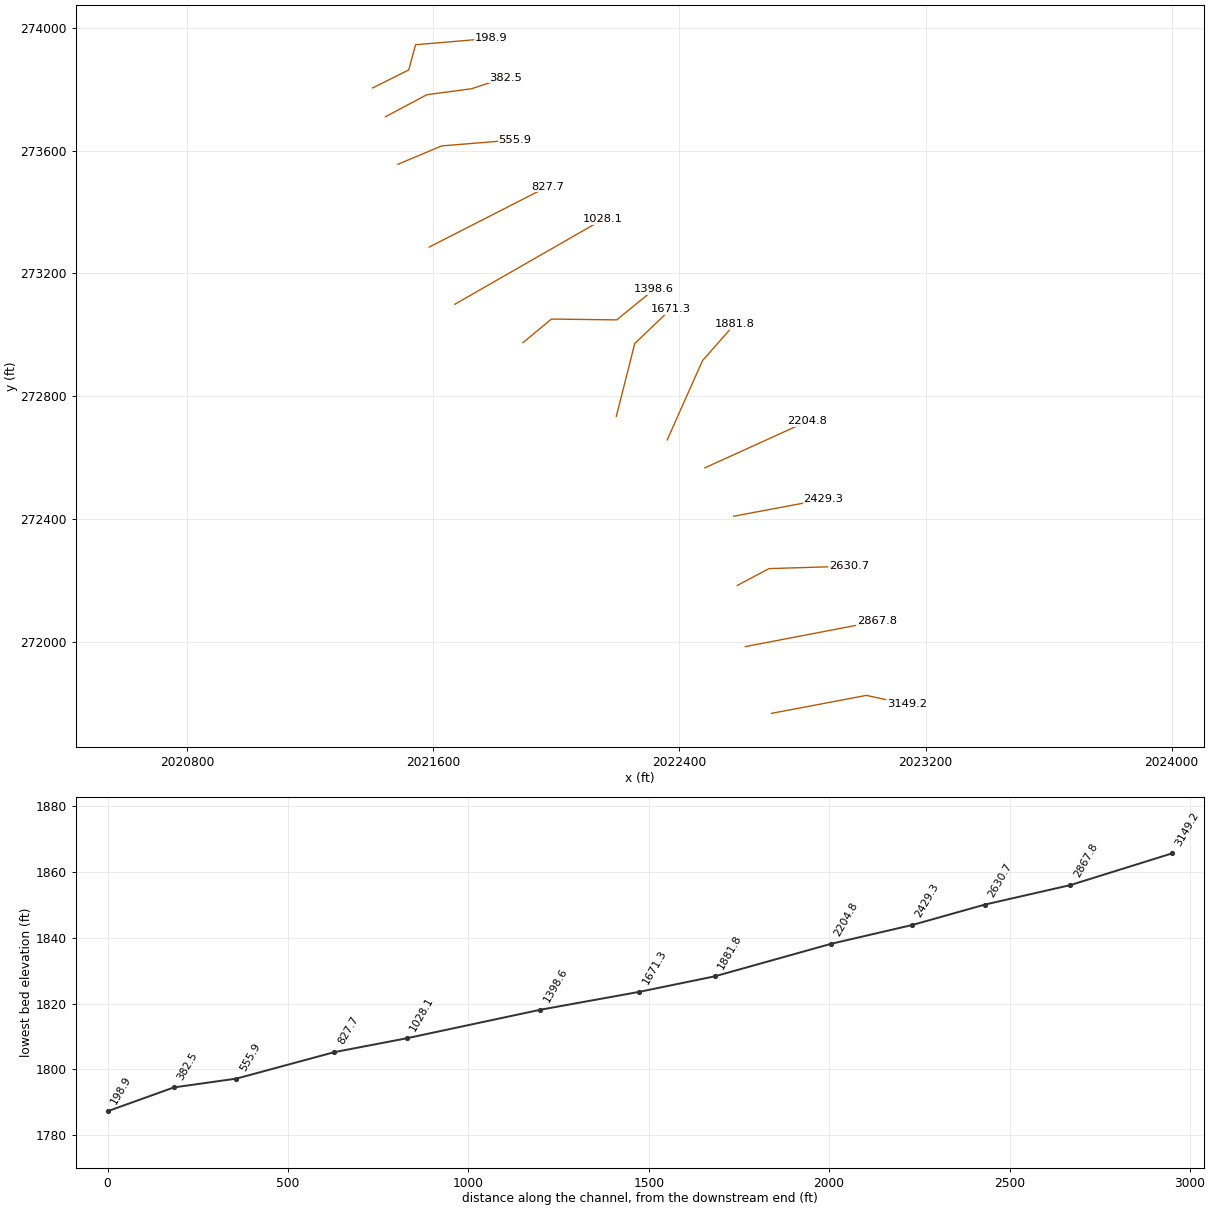
HEC-RAS study LRLCKTRIB.prj: LRLCKTRIB

--- LRLCKTRIB.g01 (geometry) --- (continued)

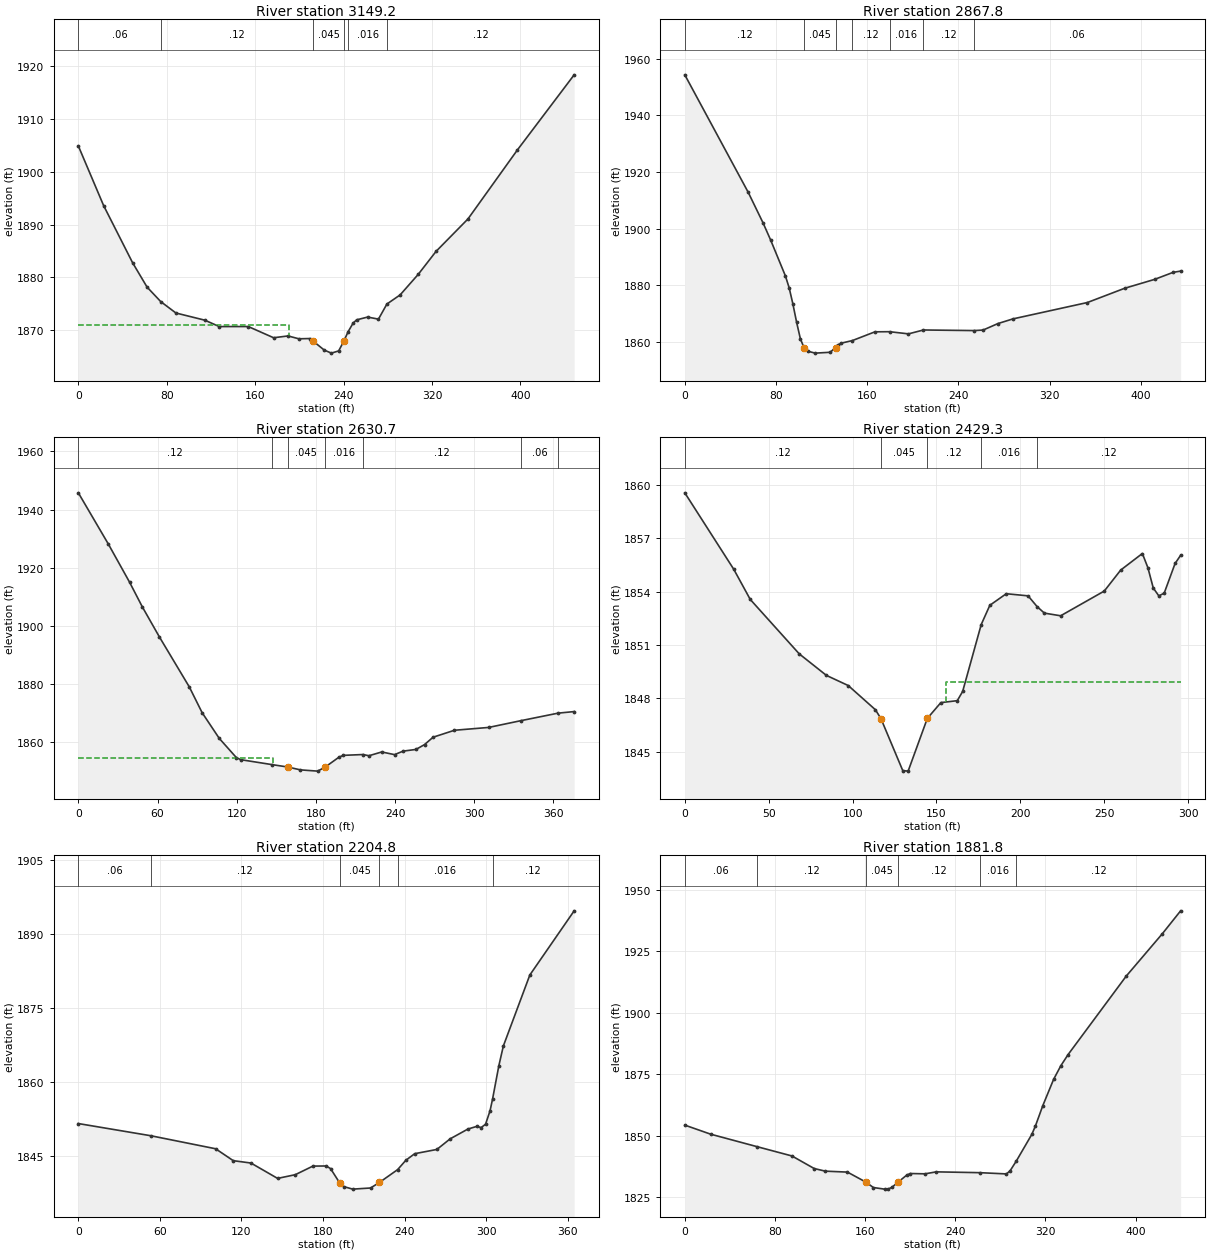
Type RM Length L Ch R = 1 ,3149.2  ,281,281.4,280.6
XS GIS Cut Line= 3
     2022699.324      271767.292     2023007.917      271825.885
     2023139.428       271797.24
#Sta/Elev= 30
       0 1904.87    22.9 1893.58    49.1 1882.78    62.2 1878.17   74.521875.437
    88.3 1873.27   114.5 1871.91   127.6  1870.7   153.8 1870.71   176.7 1868.59
   189.8 1868.93   199.6 1868.39   209.4 1868.44   212.7 1867.92   222.5 1866.26
     229 1865.68   235.6  1866.1  240.251867.949  244.131869.726   248.7 1871.37
   251.9 1871.98   261.8  1872.5   271.6 1872.11  279.241874.965   291.2 1876.69
   307.6 1880.58   323.7 1884.92   352.6 1891.06   397.4 1904.13   448.7 1918.32
#Mann= 6 ,-1 , 0
       0     .06       0   74.52     .12       0   212.7    .045       0
  240.25     .12       0  244.13    .016       0  279.24     .12       0
#XS Ineff= 2 , 0
           190.4 1870.95
Permanent Ineff=
       F       F
Bank Sta=212.7,240.25
XS Rating Curve= 0 ,0
Exp/Cntr=0.3,0.1

Type RM Length L Ch R = 1 ,2867.8  ,240.6,237,233.3
XS GIS Cut Line= 2
     2022614.688       271984.74     2023041.772      272066.771
#Sta/Elev= 30
       0 1954.28    55.6 1912.83    68.7 1901.96    75.2 1896.06    88.3 1883.25
    91.6    1879    94.8 1873.42    98.1 1866.89   101.4 1861.07   104.6 1857.96
   107.9 1856.72   114.4 1856.05   127.5 1856.35  132.28 1858.03   134.1 1858.89
   137.3 1859.58  146.881860.468   166.8 1863.57  179.551863.615   196.2 1862.85
  209.32 1864.22  253.631864.011   261.6 1864.19   274.7 1866.49   287.8 1868.13
   353.1 1873.91   385.8 1878.94     412 1882.07   428.4 1884.57   434.9    1885
#Mann= 7 ,-1 , 0
       0     .12       0   104.6    .045       0  132.28     .06       0
  146.88     .12       0  179.55    .016       0  209.32     .12       0
  253.63     .06       0
Bank Sta=104.6,132.28
XS Rating Curve= 0 ,0
Exp/Cntr=0.3,0.1

Type RM Length L Ch R = 1 ,2630.7  ,197.4,201.4,204.4
XS GIS Cut Line= 3
     2022588.647      272183.958     2022691.511      272238.646
     2022950.626      272246.458
#Sta/Elev= 30
       0 1945.73    22.6 1928.24    38.8 1915.05    48.5 1906.54    61.5 1896.17
    84.1 1879.04    93.8  1870.2   106.8 1861.36   119.7 1854.79     123 1854.06
  146.651852.367   158.6 1851.54   168.3 1850.55   181.3 1850.12  186.81 1851.43
   197.5 1854.92   200.8 1855.54  215.741855.821   220.2 1855.41   229.9  1856.7
   239.6 1855.79   246.1 1856.99   255.8 1857.57   262.3 1859.23   268.8 1861.77
     285 1864.16   310.9 1865.13  335.141867.436   363.51870.037   375.7 1870.58
#Mann= 7 ,-1 , 0
       0     .12       0  146.65     .06       0   158.6    .045       0
  186.81    .016       0  215.74     .12       0  335.14     .06       0
   363.5     .08       0
#XS Ineff= 2 , 0
          147.78  1854.8
Permanent Ineff=
       F       F
Bank Sta=158.6,186.81
XS Rating Curve= 0 ,0
Exp/Cntr=0.3,0.1

Type RM Length L Ch R = 1 ,2429.3  ,218.6,224.5,229.6
XS GIS Cut Line= 2
     2022576.928      272409.219     2022867.292      272463.906
#Sta/Elev= 30
       0 1859.55    29.2 1855.25      39 1853.56    68.2  1850.5    84.4 1849.29
    97.4 1848.72   113.6 1847.36   116.9 1846.86   129.9 1843.94   133.1 1843.91
  144.541846.873   152.6 1847.76   162.4 1847.87   165.6 1848.39  176.661852.149
   181.8 1853.23   191.6 1853.88   204.6 1853.76  209.961853.156   214.3 1852.79
     224 1852.64     250 1854.03   259.8 1855.21   272.7 1856.14     276 1855.34
   279.2  1854.2   282.5 1853.76   285.7 1853.91   292.2 1855.58   295.5 1856.04
#Mann= 5 ,-1 , 0
       0     .12       0   116.9    .045       0  144.54     .12       0
  176.66    .016       0  209.96     .12       0
#XS Ineff= 2 , 0
                          155.73          1848.9
Permanent Ineff=
       F       F
Bank Sta=116.9,144.54
XS Rating Curve= 0 ,0
Exp/Cntr=0.3,0.1

Type RM Length L Ch R = 1 ,2204.8  ,305.1,323,339.5
XS GIS Cut Line= 2
     2022483.178      272566.771     2022815.209      272717.813
#Sta/Elev= 30
       0 1851.52   53.151849.053     101  1846.4     114 1843.98     127  1843.5
   146.6 1840.38   159.6 1841.13   172.6 1842.88   182.4  1842.9   185.6 1842.36
   192.2  1839.5   195.4  1838.7   201.9  1838.2     215 1838.43   221.5 1839.55
  234.931842.164     241 1844.07   247.5  1845.4   263.8 1846.26   273.6 1848.42
   286.6  1850.4   293.1 1850.94   296.4 1850.71   299.6 1851.38   302.9  1854.1
  304.741856.458   309.4 1863.28   312.7 1867.27   332.2  1881.7   364.8 1894.73
#Mann= 6 ,-1 , 0
       0     .06       0   53.15     .12       0   192.2    .045       0
   221.5     .12       0  234.93    .016       0  304.74     .12       0
Bank Sta=192.2,221.5
XS Rating Curve= 0 ,0
Exp/Cntr=0.3,0.1

Type RM Length L Ch R = 1 ,1881.8  ,206.4,210.5,214.1
XS GIS Cut Line= 3
     2022360.782      272657.917     2022475.365      272915.729
     2022579.532      273034.219
#Sta/Elev= 30
       0 1854.31      23 1850.62   64.071845.559    95.1 1841.77   114.8 1836.67
   124.7  1835.6   144.3 1835.22   160.8 1831.12   167.3 1828.95   177.2  1828.3
   180.4 1828.33   183.7 1829.02  189.23 1831.14   196.8 1833.96   200.1 1834.64
   213.2 1834.52   223.1 1835.32   261.71834.987   285.4 1834.48   288.6 1835.74
  294.211839.785   307.9 1850.56   311.1 1853.99   317.6  1862.2   327.2 1872.89
   333.6 1878.42   340.1    1883   391.6 1914.83   423.8 1932.14   439.9 1941.38
#Mann= 6 ,-1 , 0
       0     .06       0   64.07     .12       0   160.8    .045       0
  189.23     .12       0   261.7    .016       0  294.21     .12       0
Bank Sta=160.8,189.23
XS Rating Curve= 0 ,0
Exp/Cntr=0.3,0.1

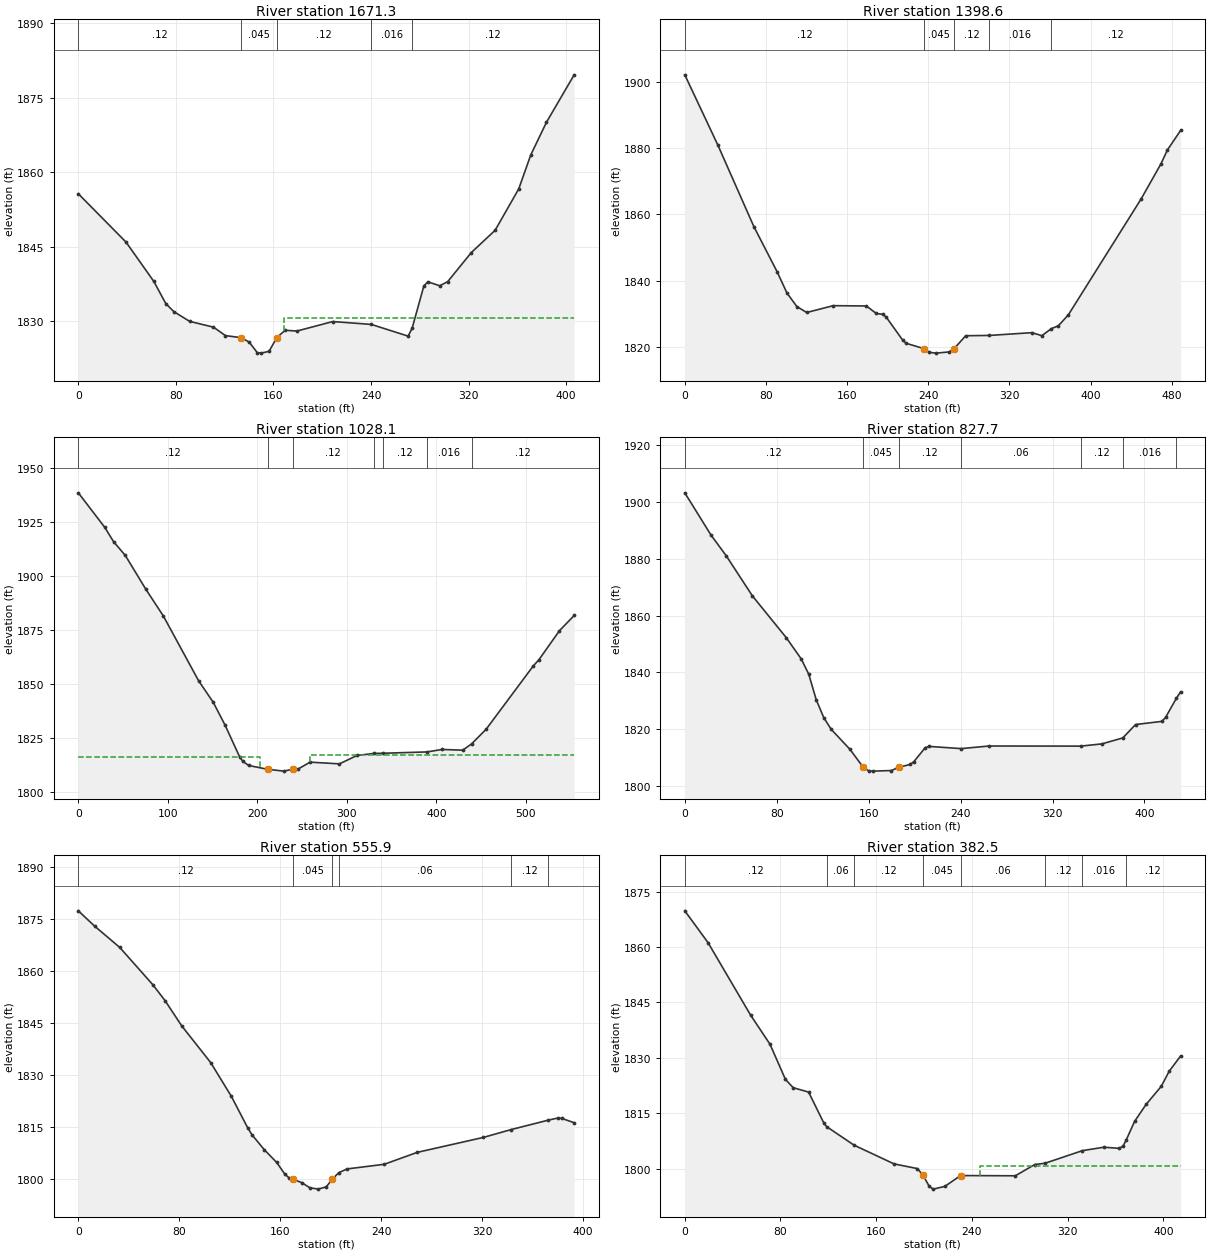
Type RM Length L Ch R = 1 ,1671.3  ,303.1,272.7,241
XS GIS Cut Line= 3
     2022195.417       272734.74     2022255.313      272971.719
     2022372.501      273083.698
#Sta/Elev= 30
       0 1855.64    39.1 1845.91    61.9 1837.99    71.7 1833.53    78.2 1831.93
    91.2 1829.95   110.8 1828.78   120.6 1827.08   133.6 1826.66   140.1 1825.77
   146.7 1823.65   149.9 1823.55   156.4 1823.92  162.671826.661   169.5 1828.15
   179.2    1828   208.6 1829.91   240.21829.333   270.4 1826.97  273.681828.581
   283.3  1837.1   286.6 1837.91   296.3 1837.12   302.8 1837.94   322.2 1843.81
   341.7 1848.29   361.1 1856.64   370.9 1863.45   383.8 1870.05   406.5  1879.6
#Mann= 5 ,-1 , 0
       0     .12       0   133.6    .045       0  162.67     .12       0
   240.2    .016       0  273.68     .12       0
#XS Ineff= 2 , 0
                          168.73         1830.54
Permanent Ineff=
       F       F
Bank Sta=133.6,162.67
XS Rating Curve= 0 ,0
Exp/Cntr=0.3,0.1

Type RM Length L Ch R = 1 ,1398.6  ,356.7,370.5,382.4
XS GIS Cut Line= 4
     2021892.032      272974.323      2021984.48      273051.146
      2022196.72      273048.542     2022317.813        273147.5
#Sta/Elev= 30
       0 1902.17    32.5 1881.02    68.2 1856.27      91 1842.72   100.7  1836.3
   110.5 1832.19   120.2 1830.41   146.3 1832.47     179 1832.38   188.8 1830.11
   195.3 1829.86   198.6    1829   214.9 1822.02   218.2 1821.11  235.861819.483
     241 1818.38   247.6 1818.14   260.6  1818.5  265.571819.516   276.9 1823.39
  300.341823.482   342.2 1824.32     352 1823.41  361.291825.517   368.3  1826.4
   378.1 1829.69   449.8 1864.67   469.3 1875.23   475.8 1879.49   488.8 1885.39
#Mann= 5 ,-1 , 0
       0     .12       0  235.86    .045       0  265.57     .12       0
  300.34    .016       0  361.29     .12       0
Bank Sta=235.86,265.57
XS Rating Curve= 0 ,0
Exp/Cntr=0.3,0.1

Type RM Length L Ch R = 1 ,1028.1  ,201.7,200.5,199.4
XS GIS Cut Line= 2
     2021670.678      273099.323     2022151.147      273375.365
#Sta/Elev= 30
       0 1938.46    29.5 1922.48    39.4  1915.8    52.5 1909.44    75.4 1893.79
    95.1 1881.31   134.4 1851.35   150.8 1841.34   163.9 1830.85   180.3 1816.04
   183.6 1814.12   190.2 1812.09  211.471810.317   229.5 1809.46   239.4  1810.3
   245.9 1810.51     259 1813.62   291.8 1812.83   311.5 1816.73  329.951817.643
  340.71 1817.75  389.711818.361   406.6  1819.5   429.5 1819.17  439.411822.064
   455.8 1828.91   508.2 1858.11   514.8 1861.14   537.7 1874.57   554.1  1881.6
#Mann= 7 ,-1 , 0
       0     .12       0  211.47    .045       0   239.4     .12       0
  329.95     .06       0  340.71     .12       0  389.71    .016       0
  439.41     .12       0
#XS Ineff= 2 , 0
           203.1 1816.08  259.44         1817.03
Permanent Ineff=
       F       F
Bank Sta=211.47,239.4
XS Rating Curve= 0 ,0
Exp/Cntr=0.3,0.1

Type RM Length L Ch R = 1 ,827.7   ,280.1,271.8,262.5
XS GIS Cut Line= 2
     2021587.345      273285.521     2021971.459      273482.135
#Sta/Elev= 30
       0 1903.19    22.9 1888.27      36 1881.07    58.8 1866.94    88.3 1852.22
   101.3 1844.75   107.9 1839.34   114.4 1830.34     121 1824.02   127.5 1819.92
   143.8 1812.89  155.311806.587   160.2 1805.31   163.4 1805.25   179.8 1805.46
   186.3 1806.62   196.1 1807.59   199.4 1808.61   209.2 1813.48   212.5 1813.95
  240.611813.173   264.8 1814.09  344.561814.055   362.9 1814.83  381.151816.935
   392.3 1821.65   415.2 1822.76   418.4 1824.15  427.761830.859   431.5 1833.16
#Mann= 7 ,-1 , 0
       0     .12       0  155.31    .045       0   186.3     .12       0
  240.61     .06       0  344.56     .12       0  381.15    .016       0
  427.76     .12       0
Bank Sta=155.31,186.3
XS Rating Curve= 0 ,0
Exp/Cntr=0.3,0.1

Type RM Length L Ch R = 1 ,555.9   ,172.1,173.4,174.4
XS GIS Cut Line= 3
     2021485.782      273555.052     2021627.709      273614.948
      2021865.99      273634.479
#Sta/Elev= 30
       0 1877.44    13.1 1872.97    32.8  1866.9      59 1856.16    68.8 1851.53
    81.9  1844.3   104.9  1833.7   121.3 1823.96   134.4 1814.78   137.7 1812.85
   147.5 1808.53   157.3 1804.87   163.9 1801.42   167.2 1800.42   170.4 1800.01
     177 1799.08   183.5  1797.6   190.1 1797.19   196.6 1797.86  201.34 1800.06
  206.451801.921     213 1803.01   242.5 1804.35   268.7 1807.79   321.1  1812.1
   342.9 1814.34  372.541817.076     380 1817.68   383.3 1817.58   393.1 1816.34
#Mann= 6 ,-1 , 0
       0     .12       0   170.4    .045       0  201.34     .12       0
  206.45     .06       0   342.9     .12       0  372.54    .016       0
Bank Sta=170.4,201.34
XS Rating Curve= 0 ,0
Exp/Cntr=0.3,0.1

Type RM Length L Ch R = 1 ,382.5   ,156.5,183.6,210
XS GIS Cut Line= 4
     2021445.417         273710.     2021579.532      273781.615
     2021725.365      273801.146      2021834.74      273837.604
#Sta/Elev= 30
       0 1869.79    19.4  1861.2      55 1841.58    71.2 1833.72    84.1 1824.22
    90.6 1821.95   103.5 1820.76   116.4 1812.28  118.66 1811.39  141.631806.383
   174.9 1801.34   194.5 1800.06   199.21798.252   204.3 1795.29   207.6 1794.51
   217.4 1795.25   230.5 1798.18   276.3 1798.12   292.6 1801.17  301.231801.519
  332.361804.917   350.4 1805.85   363.2 1805.54   366.4 1806.19  368.921807.734
     376 1812.82   385.6 1817.41   398.4 1822.35   404.9 1826.39   414.5 1830.52
#Mann= 8 ,-1 , 0
       0     .12       0  118.66     .06       0  141.63     .12       0
   199.2    .045       0   230.5     .06       0  301.23     .12       0
  332.36    .016       0  368.92     .12       0
#XS Ineff= 2 , 0
                          246.65         1800.78
Permanent Ineff=
       F       F
Bank Sta=199.2,230.5
XS Rating Curve= 0 ,0
Exp/Cntr=0.3,0.1

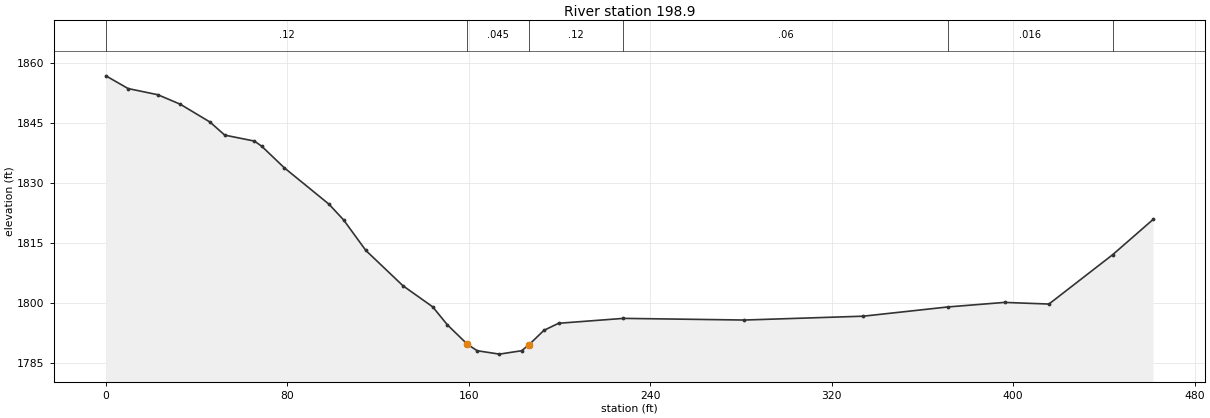
Type RM Length L Ch R = 1 ,198.9   ,218.2,198.9,178.1
XS GIS Cut Line= 4
     2021403.751       273803.75     2021520.938      273862.344
     2021543.074      273944.375     2021787.865      273965.208
#Sta/Elev= 30
       0 1856.74     9.8 1853.56    22.9 1852.02    32.8 1849.65    45.9  1845.2
    52.4 1841.94    65.5 1840.45    68.8 1839.12    78.6 1833.81    98.3 1824.73
   104.8 1820.78   114.6 1813.16     131 1804.33   144.1 1799.07   150.6 1794.56
  159.371789.744   163.7 1788.12   173.5 1787.27   183.3 1788.12   186.6 1789.64
   193.1  1793.2   199.6 1794.97  228.211796.195   281.5 1795.78   333.9 1796.74
  371.251799.048   396.2 1800.18   415.8 1799.77  443.951812.117   461.7 1820.88
#Mann= 6 ,-1 , 0
       0     .12       0  159.37    .045       0   186.6     .12       0
  228.21     .06       0  371.25    .016       0  443.95     .12       0
Bank Sta=159.37,186.6
XS Rating Curve= 0 ,0
Exp/Cntr=0.3,0.1

Chan Stop Cuts=-1
Use User Specified Reach Order=0
Composite Channel Slope=5